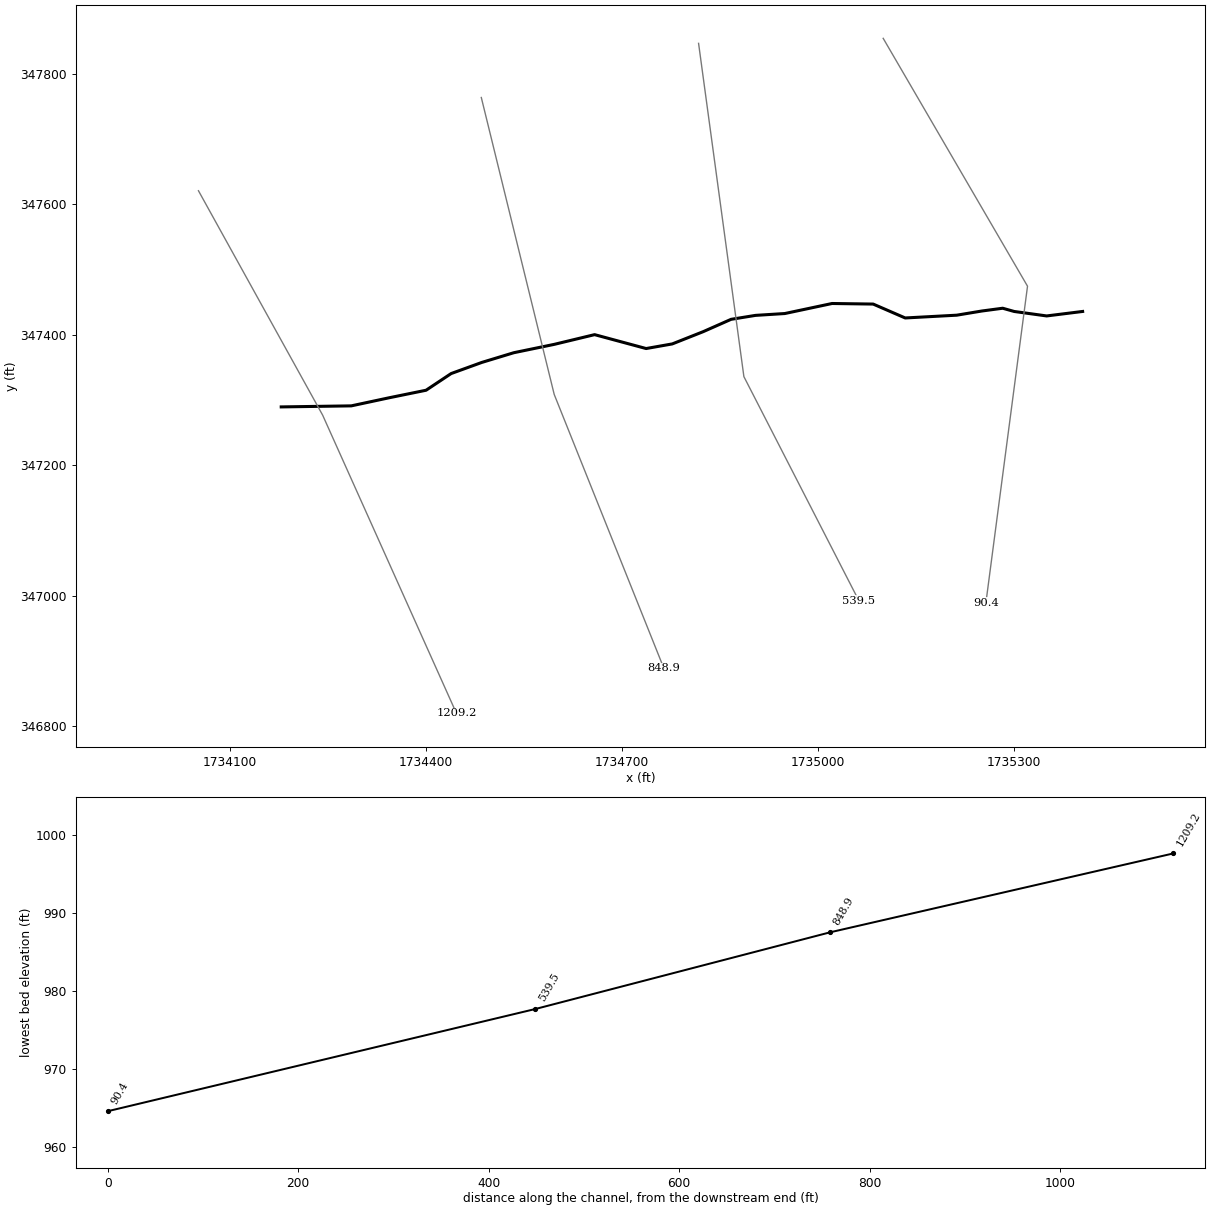
--- NP12.prj (project) ---

Proj Title=NP12
Current Plan=p01
Default Exp/Contr=0,0
English Units
Geom File=g01
Flow File=f01
Plan File=p01
BEGIN DESCRIPTION:
END DESCRIPTION:
DSS Export Rating Curves= 0
DSS Export Rating Curve Sorted= 0
DSS Export Volume Flow Curves= 0
DXF OffsetX= 0
DXF OffsetY= 0
DXF ScaleX= 0
DXF ScaleY= 0

--- NP12.p01 (plan) ---

Plan Title=Floodplain
Program Version=4.00
Geom File=g01
Flow File=f01
K Sum by GR=0
Std Step Tol=0.01
Critical Tol=0.01
Num of Std Step Trials=20
Max Error Tol=0.3
Flow Tol Ratio=0.001
Split Flow NTrial=30
Split Flow Tol=0.02
Split Flow Ratio=0.02
Log Output Level=0
Friction Slope Method=1
Unsteady Friction Slope Method=2
Unsteady Bridges Friction Slope Method=1
Global Log Level=0
CheckData=False
Run HTab=0
Run UNet=0
Run PostProcess=0
UNET Theta=0
UNET Theta Warmup=0
UNET ZTol=0
UNET ZSATol=0
UNET MxIter=0
UNET MaxInSteps=0
UNET DtIC=0
UNET DtMin=0
UNET MaxCRTS=0
UNET WFStab=0
UNET SFStab=0
UNET WFX=0
UNET SFX=0
UNET DSS MLevel=0
UNET DZMax Abort=0
UNET Convert EG Bridges=0
UNET Use Existing IB Tables=0
UNET Froude Limit=0
UNET Froude Power=0
Write IC File=0
Echo Input=False
Echo Output=False
Write Detailed=0

--- NP12.f01 (steady flow) ---

Flow Title=NFF Regression Equation
Program Version=4.00
Number of Profiles=1
Profile Names=P100yr
River Rch & RM=NP12,Main      ,1209.2
353.1403
River Rch & RM=NP12,Main      ,90.4
387.0024
River Rch & RM=NP12,Main      ,90.4
393.5328
Boundary for River Rch & Prof#=NP12,Main      ,1
Up Type=0
Dn Type=3
Dn Slope=0.026626

--- NP12.g01 (geometry) ---

Geom Title=USGS 3m DEM
Program Version=4.00

River Reach=NP12            ,Main
Reach XY= 24
     1734178.162      347289.245     1734285.416      347290.859
     1734342.763      347303.153     1734399.836      347314.823
     1734438.202      347340.401     1734485.094      347357.452
     1734534.118      347372.373     1734595.931      347385.162
     1734657.744      347400.082     1734736.609      347378.767
     1734776.636      347385.859     1734824.102      347404.717
     1734866.597       347423.56     1734904.003      347429.627
     1734948.812      347432.451     1735021.147      347447.844
     1735084.039      347446.974     1735133.063       347425.66
     1735211.927      347429.923     1735250.294      347436.317
     1735282.266       347440.58     1735299.816      347435.633
     1735349.554      347428.764     1735404.602      347435.644

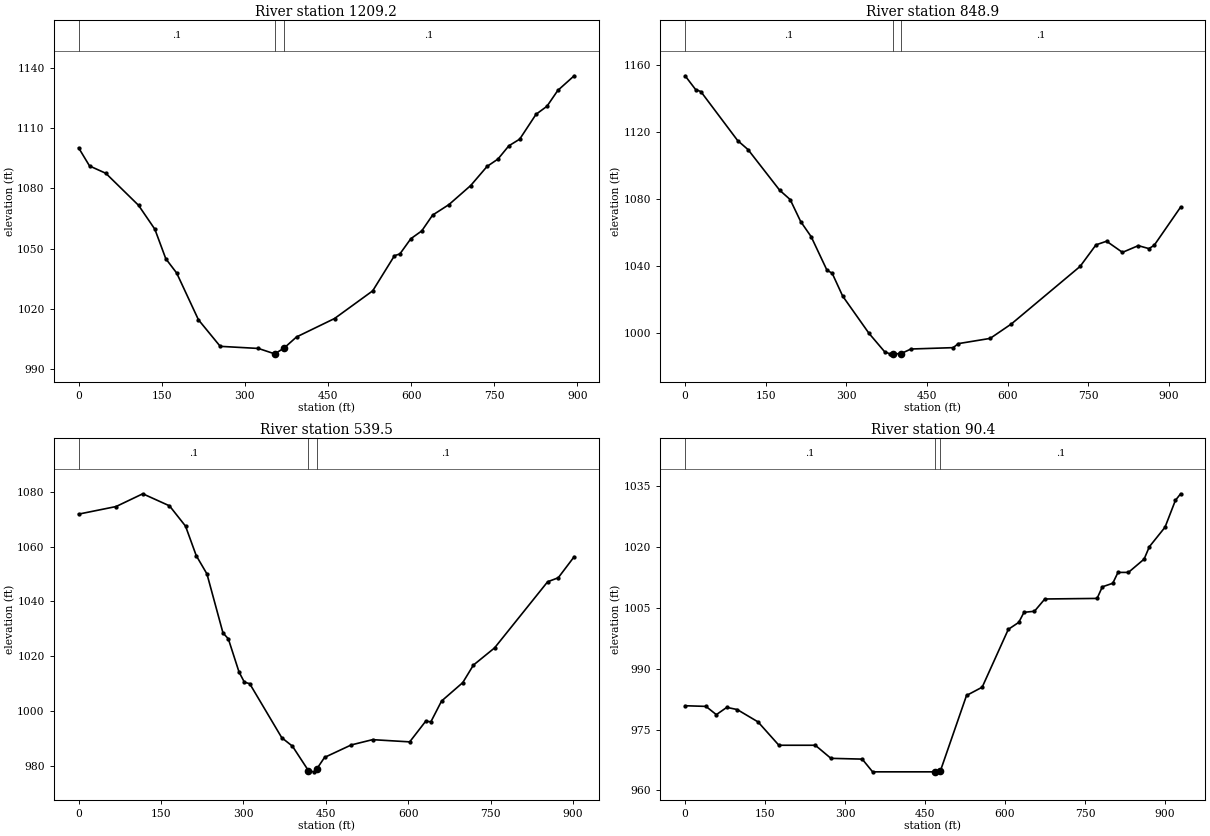
Type RM Length L Ch R = 1 ,1209.2  ,367.117,360.294,354.391
XS GIS Cut Line= 3
     1734051.497      347620.782     1734241.556      347276.621
     1734446.364      346819.252
#Sta/Elev= 30
       0 1100.09    19.7 1091.08    49.1 1087.43   108.1 1071.52   137.6 1059.61
   157.3 1044.94   176.9 1037.86   216.2  1014.6   255.5 1001.38   324.4 1000.33
   353.8  997.65   370.3 1000.41   393.2 1006.04   461.9 1015.22   530.7 1028.98
     570 1046.46   579.8 1047.34   599.5  1054.9   619.2 1058.78   638.8 1066.64
   668.3 1071.87   707.6 1081.36   737.1 1090.85   756.7  1094.5   776.4  1101.1
     796 1104.42   825.5 1116.78   845.2 1120.77   864.8 1128.66   894.3 1135.93
#Mann= 3 , 0 , 0
       0      .1       0   353.8    .045       0   370.3      .1       0
Bank Sta=353.8,370.3
XS Rating Curve= 0 ,0
Exp/Cntr=0.3,0.1

Type RM Length L Ch R = 1 ,848.9   ,311.875,309.406,306.938
XS GIS Cut Line= 3
     1734484.346      347763.772      1734595.93      347308.387
     1734763.834      346888.132
#Sta/Elev= 30
       0 1153.39    19.5  1145.2    29.3 1143.96    97.7 1114.75   117.2 1109.31
   175.8 1085.14   195.4 1079.54   214.9 1066.45   234.4 1057.41   263.7 1037.47
   273.5 1035.59     293 1021.97   341.9  999.77   371.2  988.71   380.9  987.53
   386.1  987.53   401.1  987.62     420  990.41   498.4  991.22   508.2  993.63
   567.2  996.74   606.6 1005.34   734.5 1039.69     764 1052.54   783.7  1054.7
   813.2 1048.06   842.7 1052.07   862.4  1050.3   872.2 1052.26   921.4 1075.08
#Mann= 3 , 0 , 0
       0      .1       0   386.1    .045       0   401.1      .1       0
Bank Sta=386.1,401.1
XS Rating Curve= 0 ,0
Exp/Cntr=0.3,0.1

Type RM Length L Ch R = 1 ,539.5   ,455.11,449.076,443.041
XS GIS Cut Line= 3
     1734816.868      347846.797     1734886.214      347335.694
     1735062.288      346991.839
#Sta/Elev= 30
       0 1071.95    68.1 1074.72   116.8 1079.39   165.4 1074.98   194.6 1067.56
   214.1 1056.77   233.6 1050.07   262.8 1028.48   272.5 1026.35     292  1014.2
   301.7 1010.48   311.4 1009.94   369.8  990.17   389.3  987.06   418.4  978.11
   428.2  977.69   433.4  978.73   447.7  982.97   496.3  987.53   535.1  989.46
   602.7  988.65   631.7  996.18   641.3  996.01   660.7 1003.59   699.3 1010.33
   718.6 1016.72   757.2 1023.02   853.8 1047.21   873.1 1048.67   902.1 1056.37
#Mann= 3 , 0 , 0
       0      .1       0   418.4    .045       0   433.4      .1       0
Bank Sta=418.4,433.4
XS Rating Curve= 0 ,0
Exp/Cntr=0.3,0.1

Type RM Length L Ch R = 1 ,90.4    ,84.683,90.449,96.215
XS GIS Cut Line= 3
     1735099.388      347854.502     1735320.266      347474.385
     1735256.558      346988.732
#Sta/Elev= 30
       0  980.88    39.1  980.72    58.6  978.68    78.2  980.48    97.7  979.94
   136.8  976.89   175.9  971.13   244.2  971.13   273.5   967.9   332.2  967.71
   351.7  964.57     469  964.57   478.8  964.79   527.8  983.41   557.2  985.46
   606.2  999.73   625.8 1001.45   635.6 1003.93   655.2 1004.19   674.7 1007.22
   772.7 1007.36   782.5 1010.22   802.1  1011.1   811.9 1013.78   831.5 1013.78
   860.9 1017.06   870.7 1020.11   900.1 1024.93   919.6 1031.56   929.4 1033.18
#Mann= 3 , 0 , 0
       0      .1       0     469    .045       0   478.8      .1       0
Bank Sta=469,478.8
XS Rating Curve= 0 ,0
Exp/Cntr=0.3,0.1

Chan Stop Cuts=-1
Use User Specified Reach Order=0